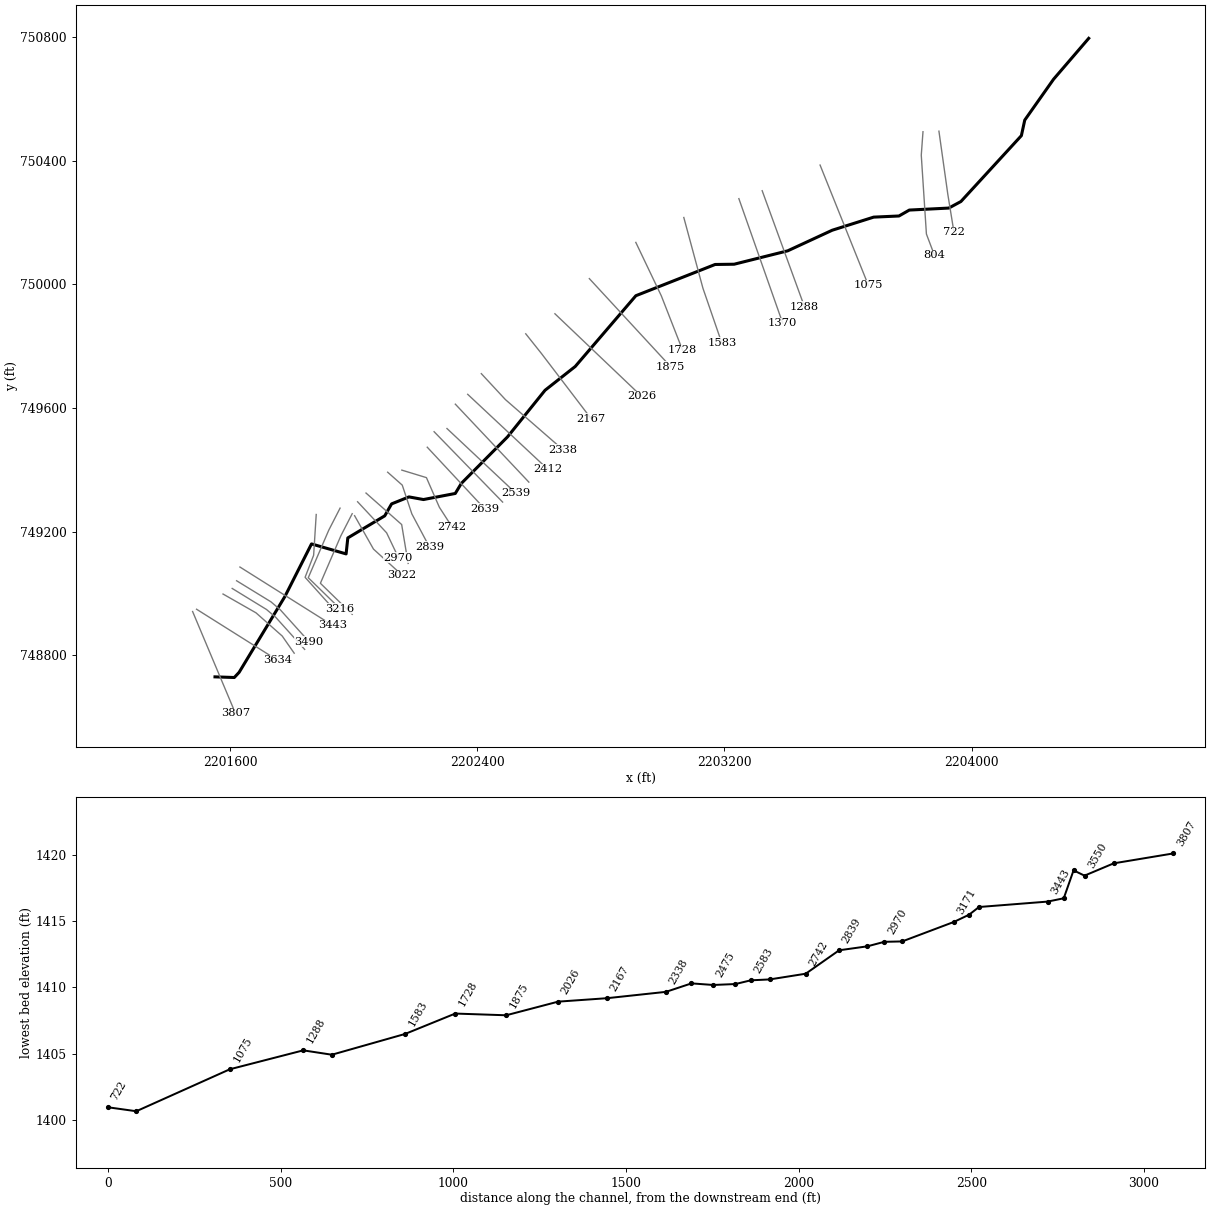
--- PECKSRNT2.prj (project) ---

Proj Title=PECKSRNT2
Current Plan=p01
Default Exp/Contr=0,0
English Units
Geom File=g01
Flow File=f01
Plan File=p01
BEGIN DESCRIPTION:
---------- MODELED AS PART OF WVEMD CTP PROGRAM, 2023----------
Stream Name: Pecks Run Tributary 2
Flood Zone:  AFH
Upshur County, WV
HEC-RAS Version: RAS 6.3
Vertical Datum: NAVD88
Projection: NAD 1983 StatePlane West Virginia S FIPS 4702 (US Feet)
Terrain: 1-meter LIDAR (FEMA Region III 3DEP collected 2016-2018)
Land Use: 2019 NLCD
Hydrologic Method:
WV SIR2010-5033 regression equations
Additional Model Notes:
None
END DESCRIPTION:
DSS Export Rating Curves= 0
DSS Export Rating Curve Sorted= 0
DSS Export Volume Flow Curves= 0
DXF OffsetX= 0
DXF OffsetY= 0
DXF ScaleX= 0
DXF ScaleY= 0

--- PECKSRNT2.p01 (plan) ---

Plan Title=Floodplain
Program Version=6.30
Short Identifier=Floodplain
Geom File=g01
Flow File=f01
Subcritical Flow
K Sum by GR= 0
Std Step Tol= 0.01
Critical Tol= 0.01
Num of Std Step Trials= 20
Max Error Tol= 0.3
Flow Tol Ratio= 0.001
Split Flow NTrial= 30
Split Flow Tol= 0.02
Split Flow Ratio= 0.02
Log Output Level= 0
Friction Slope Method= 1
Unsteady Friction Slope Method= 2
Unsteady Bridges Friction Slope Method= 1
Parabolic Critical Depth
Global Vel Dist= 0 , 0 , 0
Global Log Level= 0
CheckData=False
Encroach Param=-1 ,0,0, 0
Mapping Interval=1HOUR
Computation Time Step Use Courant=        0
Computation Time Step Use Time Series=    0
Computation Time Step Count To Double=0
Computation Time Step Max Doubling=0
Computation Time Step Max Halving=0
Computation Time Step Residence Courant=0
Run HTab= 0
Run UNet= 0
Run Sediment= 0
Run PostProcess= 0
Run WQNet= 0
Run RASMapper=-1
UNET Theta= 0
UNET Theta Warmup= 0
UNET ZTol= 0
UNET ZSATol= 0
UNET MxIter= 0
UNET Max Iter WO Improvement= 0
UNET MaxInSteps= 0
UNET DtIC= 0
UNET DtMin= 0
UNET MaxCRTS= 0
UNET WFStab= 0
UNET SFStab= 0
UNET WFX= 1
UNET SFX= 1
UNET Gravity=32.17405
UNET 1D Methodology=Finite Difference
UNET DSS MLevel= 1
UNET Pardiso=0
UNET DZMax Abort= 0
UNET Use Existing IB Tables= 0
UNET Froude Reduction=False
UNET Froude Limit= 0
UNET Froude Power= 0
UNET D1 Cores= 0
UNET WindReference=Eulerian
UNET WindDragFormulation=Hsu (1988)
UNET D2 Coriolis=0
UNET D2 Cores= 0
UNET D2 Theta= 1
UNET D2 Theta Warmup= 1
UNET D2 Z Tol= 0.01
UNET D2 Volume Tol= 0.01
UNET D2 Max Iterations= 20
UNET D2 Equation= 0
UNET D2 RampUpFraction=0.1
UNET D2 TimeSlices= 1
UNET D2 Turbulence Formulation=Non-Conservative (original)
UNET D2 Eddy Viscosity=0.3
UNET D2 Transverse Eddy Viscosity=0.1
UNET D2 Smagorinsky Mixing=0
UNET D2 BCVolumeCheck=0
UNET D2 Cores=0
UNET D2 SolverType=PARDISO (Direct)
UNET D2 Minimum Iterations= 3
UNET D2 Maximum Iterations= 30
UNET D2 Restart Number= 10
UNET D2 Relaxation Coeff=1.3
UNET D2 SOR Precondition Iterations= 10
UNET D2 ILUT Maximum Fill= 8
UNET D2 ILUT Tolerance=1E-08
UNET D2 Convergence Tolerance=0.00001
UNET D1D2 MaxIter= 0
UNET D1D2 ZTol=0.01
UNET D1D2 QTol=0.1
UNET D1D2 MinQTol=1
Write IC File= 0
Write IC File at Fixed DateTime=0
Write IC File at Sim End=0
Echo Input=False
Echo Parameters=False
Echo Output=False
Write Detailed= 0
HDF Write Warmup=0
HDF Write Time Slices=0
HDF Flush=0
HDF Compression= 1
HDF Chunk Size= 1
HDF Spatial Parts= 1
HDF Use Max Rows=0
HDF Fixed Rows= 1
Calibration Method= 0
Calibration Iterations= 20
Calibration Max Change=0.05
Calibration Tolerance=0.2
Calibration Maximum=1.5
Calibration Minimum=0.5
Calibration Optimization Method= 1
WQ AD Non Conservative
WQ ULTIMATE=-1
WQ Max Comp Step=1HOUR
WQ Output Interval=15MIN
WQ Output Selected Increments= 0
WQ Output face flow=0
WQ Output face velocity=0
WQ Output face area=0
WQ Output face dispersion=0
WQ Output cell volume=0
WQ Output cell surface area=0
WQ Output cell continuity=0
WQ Output cumulative cell continuity=0
WQ Output face conc=0
WQ Output face dconc_dx=0
WQ Output face courant=0
WQ Output face peclet=0
WQ Output face adv mass=0
WQ Output face disp mass=0
WQ Output cell mass=0
WQ Output cell source sink temp=0
WQ Output nsm pathways=0
WQ Output nsm derived pathways=0
WQ Create Restart=0
WQ Fixed Restart=0
WQ System Summary=0
WQ Write To DSS=0
Sorting and Armoring Iterations= 10
XS Update Threshold= 0.02
Bed Roughness Predictor= 0
Hydraulics Update Threshold= 0.02
Energy Slope Method= 1
Volume Change Method= 1
Sediment Retention Method= 0
Sediment TS Multiplier= 1
Warm Up Method= 0
XS Weighting Method= 0
Number of US Weighted Cross Sections= 1
Number of DS Weighted Cross Sections= 1
Upstream XS Weight=0
Main XS Weight=1
Downstream XS Weight=0
Number of DS XS's Weighted with US Boundary= 1
Upstream Boundary Weight= 1
Weight of XSs Associated with US Boundary= 0
Number of US XS's Weighted with DS Boundary= 1
Downstream Boundary Weight= 0.5
Weight of XSs Associated with DS Boundary= 0.5
Percentile Method= 0
Sediment Output Level= 3
Mass or Volume Output= 0
Output Increment Type= 1
Profile and TS Output Increment= 1
Transport Output Increment 1
XS Output Flag= 0
XS Output Increment= 10
Read HDF5 Sediment Hotstart= 0
Sediment Hotstart Type= 0
Write Gradation File= 0
Read Gradation Hotstart= 0
Write HDF5 File= 1
Write Binary Output= 1
Write DSS Sediment File= 0
DSS Sediment Output Type= 1
SV Curve= 0
Specific Gage Flag= 0
Subcell Erosion Methods= 0
Subcell Deposition Methods= 0
Advection Scheme= 1
Matrix Solver= 0
Implicit Weighting Factor= 1
Maximum Outer Loop Convergence Iterations= 5
Convergence Maximum Absolute= 0.001
Convergence RMSE= 0.0001
Grain Fractions Max Abs Error= 0.001
Max Subgrid Regions= 1
Max Subgrid Length Scale= 3.402823E+38
Initial Layer Thickness= 3.402823E+38
Min Layer Thickness= 3.402823E+38
Max Layer Thickness= 3.402823E+38
Number of Layers= 5

--- PECKSRNT2.f01 (steady flow) ---

Flow Title=Flows
Program Version=6.31
Number of Profiles= 1
Profile Names=01pct
River Rch & RM=PECKSRNT2,Main            ,3807
     216
River Rch & RM=PECKSRNT2,Main            ,3244
     245
River Rch & RM=PECKSRNT2,Main            ,2742
     275
River Rch & RM=PECKSRNT2,Main            ,527
     448
Boundary for River Rch & Prof#=PECKSRNT2,Main            , 1
Up Type= 0
Dn Type= 3
Dn Slope=0.00311
DSS Import GetInterval= 0
DSS Import GetPeak= 0
DSS Import FillOption= 0

--- PECKSRNT2.g01 (geometry) ---

Geom Title=Geometry
Program Version=6.31

River Reach=PECKSRNT2       ,Main
Reach XY= 30
2201551.36630708748730.146479562 2201613.8076133 748728.08187826
2201629.42082363748744.8375185432201777.54822245748990.128110364
2201863.65041603749160.3091252742201975.60807432749128.041468203
2201981.14599843749179.7580147682202100.62062901749251.189401597
 2202122.8340266749289.8837070472202178.99902061 749312.47524485
2202225.97066526749303.9473995722202328.85830629749323.580468878
2202348.62208787749356.3217664362202497.80453093749506.583928496
2202619.33584246 749657.530468332202717.09100005749734.562000021
2202913.20826335749963.4716488422203169.66679573750064.587128326
2203231.27840029750065.4160436392203404.60754126750108.754081681
2203548.61696464750175.4078601452203682.78596595750217.793674603
2203764.61927563750221.4854369162203798.08886138750240.646156177
2203925.78006934750247.0952070952203965.11927988750268.377075091
2204160.73000002750481.450000018     2204171.633750531.786000013
2204264.89400002750664.0510000142204378.61591171750796.344986878

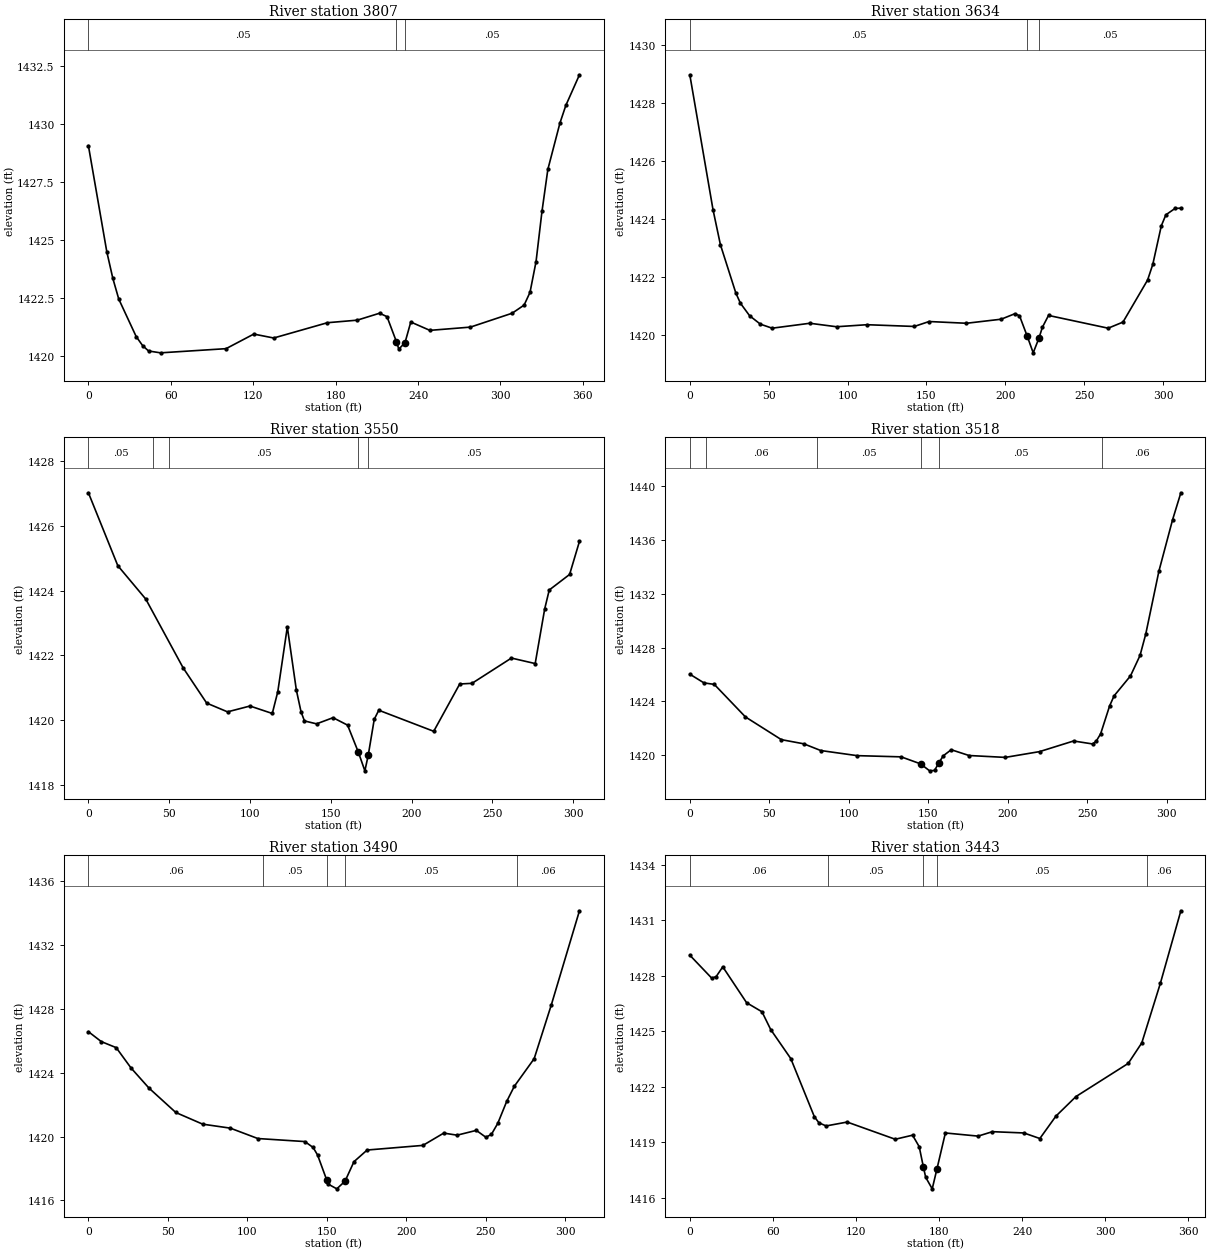
Type RM Length L Ch R = 1 ,3807    ,110.1,172.9,183.2
XS GIS Cut Line= 3
2201478.94334109 748941.548471592201550.52781481748771.293507059
2201617.59795236748612.001930396
#Sta/Elev= 30
       0 1429.06    13.4 1424.48    17.8 1423.33    22.1 1422.44    34.8 1420.82
    39.5 1420.43    43.8  1420.2    52.5 1420.12   100.2  1420.3   120.4 1420.93
   134.9 1420.76     174 1421.42   195.7 1421.53     212 1421.83   217.4 1421.68
   224.31420.592     226 1420.28   230.5 1420.56   234.7 1421.45   248.6 1421.09
   278.1 1421.23   308.5 1421.83   317.2 1422.18   321.5 1422.73   325.9 1424.06
   330.2 1426.22   334.5 1428.04   343.3 1430.04   347.6  1430.8   357.5 1432.12
#Mann= 3 ,-1,0
       0     .05       0   224.3    .045       0   230.5     .05       0
Bank Sta=224.3,230.5
XS Rating Curve= 0 ,0
Exp/Cntr(USF)=0,0
Exp/Cntr=0.3,0.1

Type RM Length L Ch R = 1 ,3634    ,86.3,84.6,83.7
XS GIS Cut Line= 2
2201491.74441036748948.9819750392201755.24240423748783.156652081
#Sta/Elev= 30
       0 1428.96    14.7 1424.31    19.4  1423.1    29.2 1421.43    32.1 1421.08
    37.9 1420.65    44.7 1420.36    52.2 1420.22    76.1 1420.39      93 1420.27
   112.3 1420.34   142.3 1420.28   151.7 1420.45   175.4 1420.39   197.4 1420.53
   206.1 1420.72     209 1420.65   213.91419.944   217.7 1419.37   221.41419.888
   223.5 1420.25   227.4 1420.66   265.2 1420.22   274.6 1420.43   290.2 1421.88
   293.5 1422.42   298.9 1423.75   301.8 1424.13   307.6 1424.35   311.3 1424.36
#Mann= 3 ,-1,0
       0     .05       0   213.9    .045       0   221.4     .05       0
Bank Sta=213.9,221.4
XS Rating Curve= 0 ,0
Exp/Cntr(USF)=0,0
Exp/Cntr=0.3,0.1

Type RM Length L Ch R = 1 ,3550    ,31.5,31.7,31.8
XS GIS Cut Line= 4
2201577.34434962748998.2076307092201684.12130025748937.318295227
2201768.83689744748862.3096935462201807.66487949748806.715082888
#Sta/Elev= 30
       0 1427.02    18.2 1424.77    35.5 1423.74    58.6 1421.62    73.2 1420.53
    86.1 1420.26     100 1420.44   113.8 1420.21   117.2 1420.88   123.1 1422.88
   128.7 1420.93   131.6 1420.26   133.7 1419.98   141.2 1419.89   151.4 1420.08
   160.4 1419.85   167.11419.011   171.1 1418.44   173.21418.927   176.9 1420.03
   179.7 1420.31   213.7 1419.66   229.8 1421.12   237.4 1421.14   261.8 1421.92
   276.5 1421.75   282.4 1423.44   285.2 1424.02   297.8  1424.5   303.9 1425.52
#Mann= 5 ,-1,0
       0     .05       0      40     .06       0      50     .05       0
   167.1    .045       0   173.2     .05       0
Bank Sta=167.1,173.2
XS Rating Curve= 0 ,0
Exp/Cntr(USF)=0,0
Exp/Cntr=0.3,0.1

Type RM Length L Ch R = 1 ,3518    ,28.3,28.4,28.2
XS GIS Cut Line= 4
2201607.04234676749016.2314520542201717.96367734748948.235156937
2201747.97321541748922.7840297142201841.42063775748819.080182971
#Sta/Elev= 30
       0 1426.03     8.9 1425.38    15.4 1425.27      35 1422.85    57.6 1421.16
    71.7 1420.85    82.4 1420.35   105.3 1419.97     133 1419.88   145.2 1419.36
   150.9 1418.84     154 1418.87   156.61419.406   159.4 1419.95   164.5 1420.41
   175.7 1419.98   198.5 1419.84   220.1 1420.27   241.5 1421.06   253.4 1420.84
   255.7 1421.04   258.5 1421.59   264.2 1423.68     267 1424.42   277.3  1425.9
   283.3 1427.42   286.9 1429.01   295.2  1433.7   303.8 1437.52     309 1439.52
#Mann= 6 ,-1,0
       0     .05       0      10     .06       0      80     .05       0
   145.2    .045       0   156.6     .05       0  259.45     .06       0
Bank Sta=145.2,156.6
XS Rating Curve= 0 ,0
Exp/Cntr(USF)=0,0
Exp/Cntr=0.3,0.1

Type RM Length L Ch R = 1 ,3490    ,44.8,46.4,47.3
XS GIS Cut Line= 4
2201621.28738065749041.1127779212201732.20871124748973.116482804
 2201762.2182493748947.6653555812201855.66567164748843.961508837
#Sta/Elev= 30
       0 1426.57     8.1 1425.95    17.5 1425.57    26.8  1424.3    38.1 1423.04
      55 1421.51    71.9 1420.78    89.3 1420.53   106.6 1419.88   136.2 1419.69
   141.4 1419.32   144.2 1418.85   149.9  1417.3     151 1417.02   156.3 1416.73
   161.5 1417.21   167.1 1418.43   175.4 1419.16   210.5 1419.45   223.6 1420.22
     232 1420.09   244.1 1420.39   250.1 1419.96   253.6 1420.14   257.6 1420.83
   263.2  1422.2     268 1423.15   280.5 1424.88   291.3 1428.25     309 1434.14
#Mann= 5 ,-1,0
       0     .06       0     110     .05       0   149.9    .045       0
   161.5     .05       0  269.45     .06       0
Bank Sta=149.9,161.5
XS Rating Curve= 0 ,0
Exp/Cntr(USF)=0,0
Exp/Cntr=0.3,0.1

Type RM Length L Ch R = 1 ,3443    ,211.8,199,188.2
XS GIS Cut Line= 2
2201632.05650614749085.5705903142201932.09091286748896.725404906
#Sta/Elev= 30
       0 1429.11    15.8 1427.87      19 1427.95    23.8 1428.48      41 1426.54
    52.1 1426.05    58.4 1425.09    72.9 1423.52    89.9 1420.38    93.2 1420.05
    98.4 1419.88   113.6 1420.09   148.3 1419.16   160.8 1419.38   165.6 1418.76
   168.6 1417.67   170.3  1417.1     175 1416.48   178.41417.551   184.5  1419.5
   208.1 1419.33   218.5 1419.57   241.2  1419.5   252.7  1419.2   264.3 1420.41
   278.8 1421.47   316.5 1423.26   326.3 1424.37   339.7 1427.59   354.5 1431.51
#Mann= 5 ,-1,0
       0     .06       0     100     .05       0   168.6    .045       0
   178.4     .05       0     330     .06       0
Bank Sta=168.6,178.4
XS Rating Curve= 0 ,0
Exp/Cntr(USF)=0,0
Exp/Cntr=0.3,0.1

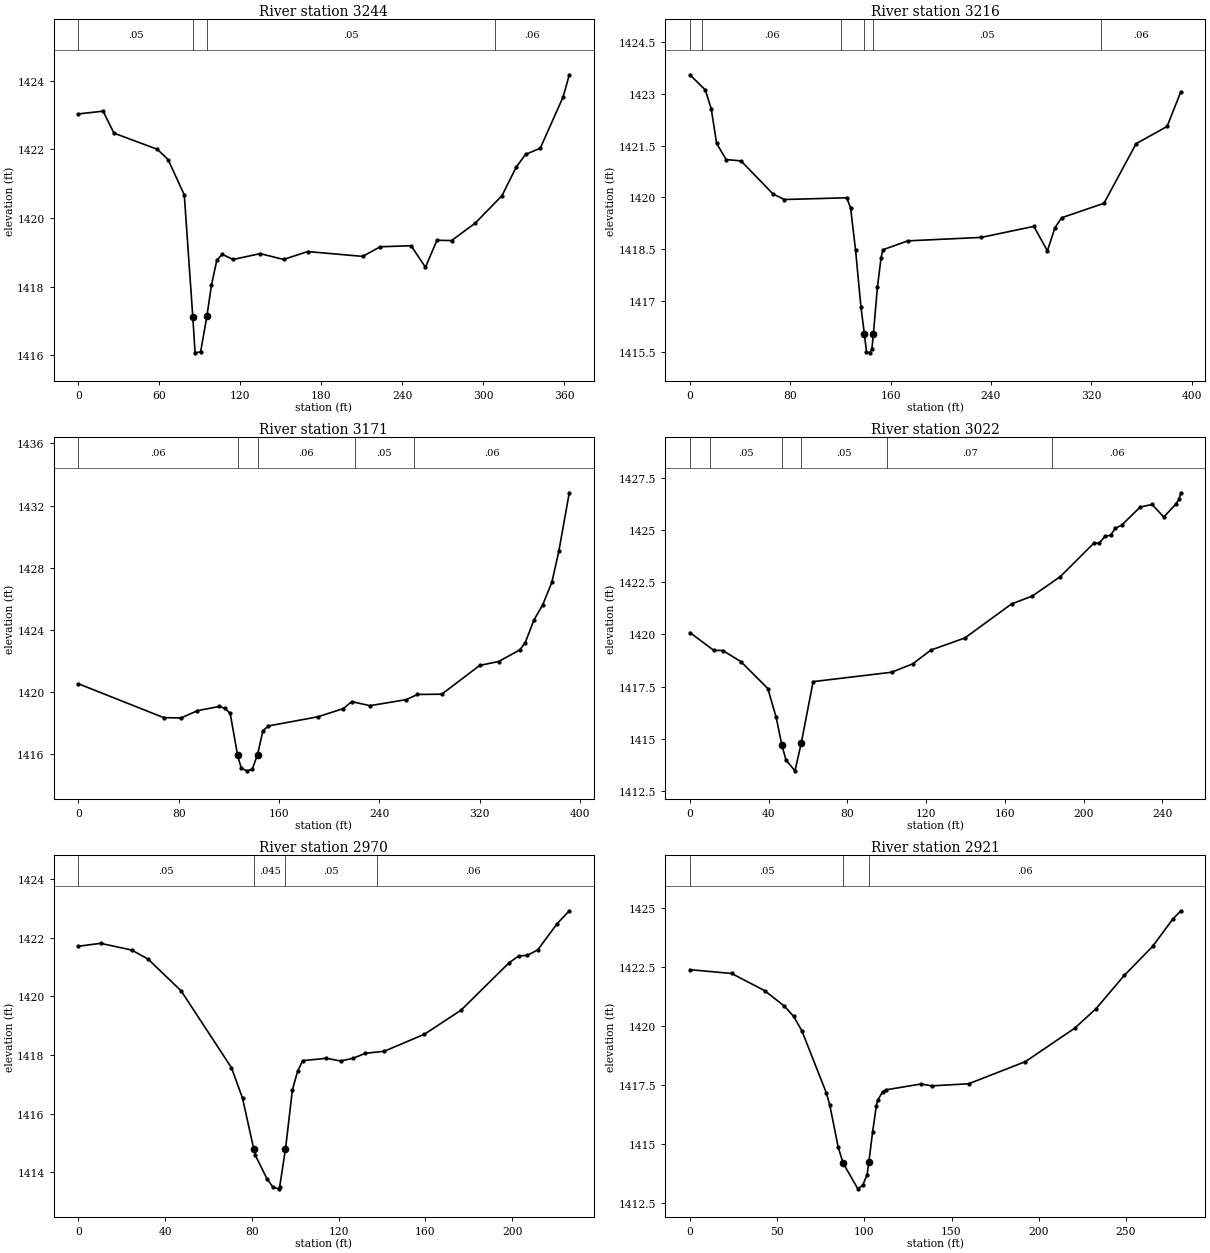
Type RM Length L Ch R = 1 ,3244    ,32.1,28.6,25.2
XS GIS Cut Line= 4
2201878.91157918 749255.552436082201870.54856132749123.674077513
2201842.88627147749052.2667711672201946.45903113748937.114448321
#Sta/Elev= 30
       0 1423.03    18.4 1423.11    26.4 1422.47    58.5    1422    66.5  1421.7
    78.5 1420.67    84.81417.117    86.5 1416.07    90.6  1416.1    95.3 1417.15
    98.6 1418.04   102.6 1418.77   106.6 1418.94   114.6 1418.79   134.8 1418.96
     152 1418.79   169.9 1419.02   210.6 1418.88   223.6 1419.16   246.5 1419.19
   257.1 1418.56   265.6 1419.35   276.4 1419.34     294 1419.85   313.8 1420.65
   324.3 1421.48   331.2 1421.85   342.1 1422.03   359.1 1423.53   363.6 1424.17
#Mann= 4 ,-1,0
       0     .05       0    84.8    .045       0    95.3     .05       0
  308.72     .06       0
Bank Sta=84.8,95.3
XS Rating Curve= 0 ,0
Exp/Cntr(USF)=0,0
Exp/Cntr=0.3,0.1

Type RM Length L Ch R = 1 ,3216    ,44,44.3,43.5
XS GIS Cut Line= 4
2201956.10866712749276.1383261982201919.44005035749204.731019852
2201853.17921653749050.9801530352201956.10866712748950.623938711
#Sta/Elev= 30
       0 1423.56    12.3 1423.12      17 1422.58    21.3 1421.57    28.9  1421.1
    40.8 1421.06    66.3  1420.1    75.3 1419.94     125 1419.99   128.1  1419.7
   132.1 1418.47   136.4 1416.81   139.1 1416.04   140.8 1415.52   143.3 1415.49
   145.1 1415.59   146.3 1416.04   149.5  1417.4   152.4 1418.24   153.8 1418.48
   173.7 1418.74   232.2 1418.84   274.2 1419.16     285 1418.45     291 1419.12
   296.3 1419.41   330.1 1419.83   355.7 1421.56   380.4 1422.06   391.4 1423.07
#Mann= 6 ,-1,0
       0     .05       0      10     .06       0  120.27     .05       0
   139.1    .045       0   146.3     .05       0  327.69     .06       0
Bank Sta=139.1,146.3
XS Rating Curve= 0 ,0
Exp/Cntr(USF)=0,0
Exp/Cntr=0.3,0.1

Type RM Length L Ch R = 1 ,3171    ,136.6,149.4,159.7
XS GIS Cut Line= 4
2201995.35052016749258.1256723452201958.68190339749186.718365999
2201892.42106957749032.9674991822201995.35052016748932.611284858
#Sta/Elev= 30
       0 1420.54    68.2 1418.36    81.9 1418.34      95 1418.81   112.4 1419.08
   116.9 1418.96   121.1 1418.63     127 1415.94   129.9 1415.12   134.2 1414.94
   138.6 1415.03   142.9 1415.98   147.2 1417.52   151.6 1417.83   190.8 1418.41
   211.2 1418.94     218 1419.39   232.5 1419.13   261.5 1419.52   270.3 1419.85
   289.8 1419.87     320 1421.72   335.1 1421.97     352 1422.72   356.3 1423.19
   363.3 1424.65   370.3 1425.63   377.5 1427.06   383.1 1429.07   391.4 1432.82
#Mann= 5 ,-1,0
       0     .06       0     127    .045       0   142.9     .06       0
  220.27     .05       0  267.69     .06       0
Bank Sta=127,142.9
XS Rating Curve= 0 ,0
Exp/Cntr(USF)=0,0
Exp/Cntr=0.3,0.1

Type RM Length L Ch R = 1 ,3022    ,48.6,51.7,54.5
XS GIS Cut Line= 3
2202003.07022895749251.6925816832202064.18459024749143.616658565
2202156.82109577749059.343170895
#Sta/Elev= 30
       0 1420.09    12.1 1419.24    16.7 1419.23    25.9  1418.7    39.6 1417.41
    43.8 1416.04    46.7 1414.72    48.8 1413.99    53.4 1413.47    56.6 1414.81
    62.6 1417.74   102.5 1418.19   113.2 1418.59   122.4 1419.25   139.7 1419.83
   163.4 1421.46     174 1421.84   188.2 1422.77   205.1 1424.36     208 1424.37
   210.8 1424.69   213.7 1424.75   216.1 1425.08   219.3 1425.23   228.8  1426.1
   234.8 1426.22   240.7 1425.62   246.7 1426.22   248.5 1426.48   249.4 1426.78
#Mann= 6 ,-1,0
       0     .06       0      10     .05       0    46.7    .045       0
    56.6     .05       0     100     .07       0  184.16     .06       0
Bank Sta=46.7,56.6
XS Rating Curve= 0 ,0
Exp/Cntr(USF)=0,0
Exp/Cntr=0.3,0.1

Type RM Length L Ch R = 1 ,2970    ,48.1,49.2,50.3
XS GIS Cut Line= 3
2202012.78527422749296.7366643222202106.71039489749196.258628254
2202144.89116039749116.128095755
#Sta/Elev= 30
       0 1421.71    10.3 1421.81    24.7 1421.58    32.2 1421.27    47.4 1420.19
    70.6 1417.57    75.7 1416.53    80.91414.791    81.5  1414.6      87 1413.78
    89.8 1413.49    92.5 1413.44    92.8  1413.5    95.5 1414.79    98.7 1416.82
   101.1 1417.45   103.4 1417.81   114.4 1417.89   120.9  1417.8   126.6 1417.89
   132.3 1418.06     141 1418.13   159.5 1418.71   176.4 1419.53   198.6 1421.15
     203 1421.38     207  1421.4   211.8 1421.59   220.7 1422.48   226.3 1422.92
#Mann= 4 ,-1,0
       0     .05       0    80.9    .045       0    95.5     .05       0
  137.54     .06       0
Bank Sta=80.9,95.5
XS Rating Curve= 0 ,0
Exp/Cntr(USF)=0,0
Exp/Cntr=0.3,0.1

Type RM Length L Ch R = 1 ,2921    ,87.2,81.8,76.3
XS GIS Cut Line= 3
2202040.02837307749324.978495931 2202155.3860515749223.104182509
2202176.36017486  749097.2594424
#Sta/Elev= 29
       0  1422.4    23.9 1422.24    42.9 1421.51    54.1 1420.86    59.5 1420.42
    64.2 1419.81    78.3 1417.16    80.2 1416.66      85 1414.88    87.8  1414.2
    96.3  1413.1    99.1 1413.25   101.6  1413.7   102.61414.228   104.8 1415.53
   106.9 1416.62   107.6 1416.85   110.5 1417.22   112.3  1417.3   132.6 1417.55
   138.7 1417.47   159.9 1417.56   192.4  1418.5   220.7 1419.92   232.9 1420.75
   249.1 1422.16   265.3 1423.39   276.9 1424.55   281.5  1424.9
#Mann= 3 ,-1,0
       0     .05       0    87.8    .045       0   102.6     .06       0
Bank Sta=87.8,102.6
XS Rating Curve= 0 ,0
Exp/Cntr(USF)=0,0
Exp/Cntr=0.3,0.1

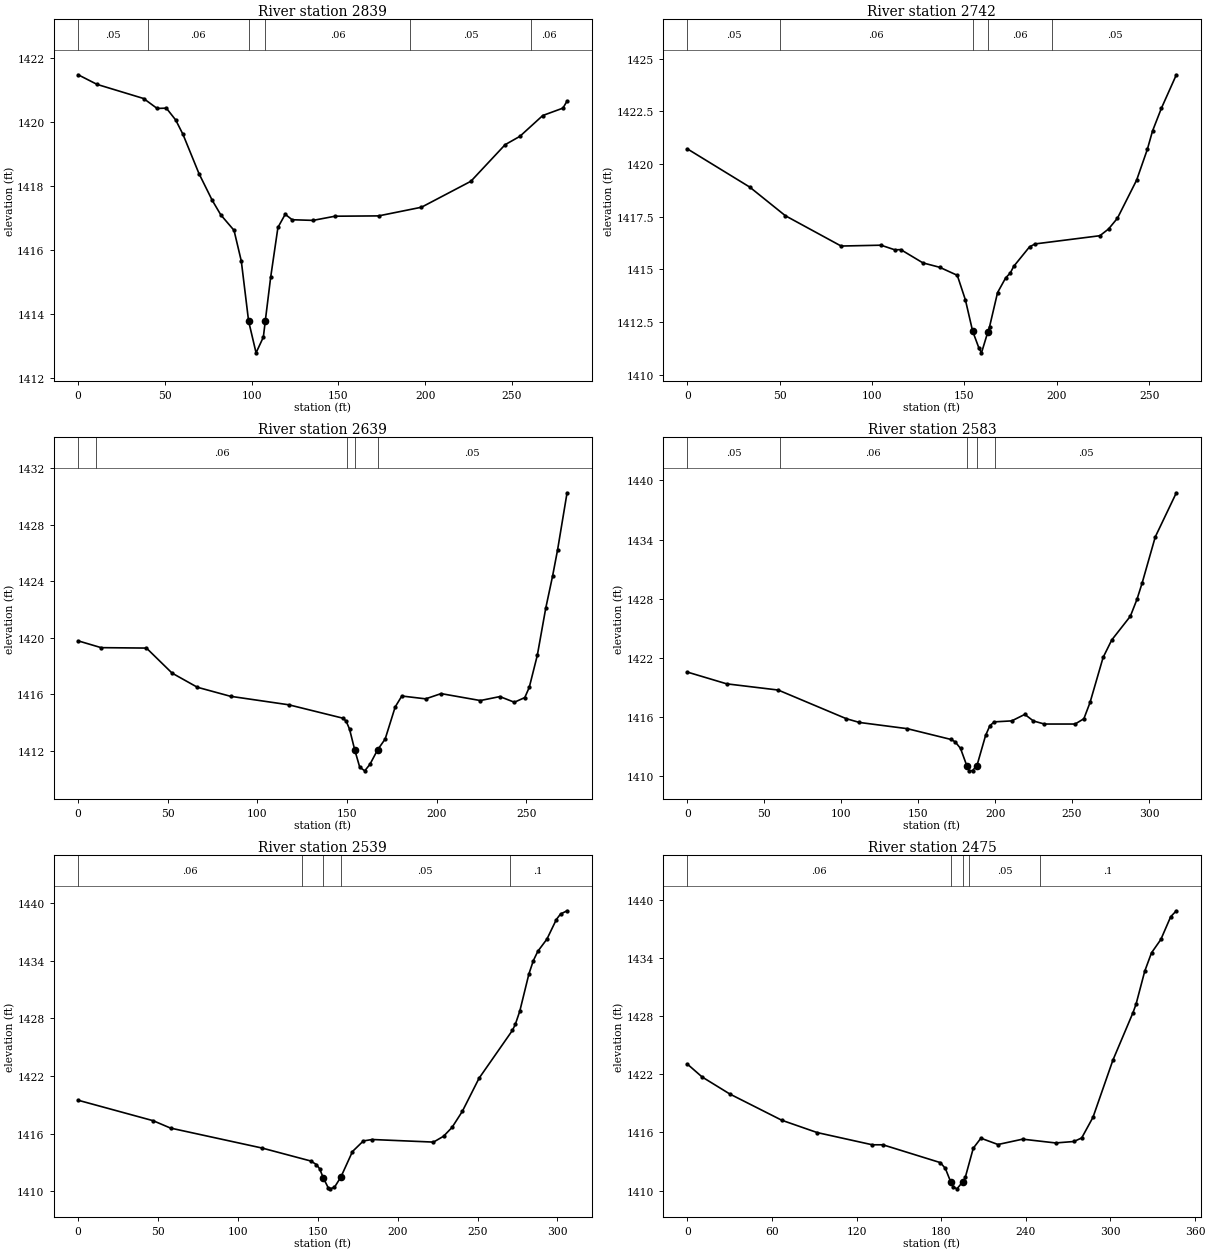
Type RM Length L Ch R = 1 ,2839    ,97.3,96.7,98.4
XS GIS Cut Line= 4
 2202110.1262352749392.3733751162202157.31801275 749350.57494358
2202188.32975227749257.5397249982202244.95988532749151.021141405
#Sta/Elev= 30
       0 1421.47    10.9 1421.17    37.7 1420.73    45.5 1420.42    50.8 1420.43
    56.2 1420.06    60.4 1419.61    69.6 1418.39    77.2 1417.56    82.2  1417.1
    89.8 1416.62      94 1415.66    98.2 1413.79   102.5  1412.8   106.7 1413.29
   107.81413.787   110.9 1415.15   115.1 1416.71   119.3 1417.12   123.3 1416.95
   135.3 1416.93     148 1417.06   173.1 1417.07   197.8 1417.34   226.3 1418.15
     246 1419.29   254.5 1419.55   267.7  1420.2   279.3 1420.43   281.7 1420.65
#Mann= 6 ,-1,0
       0     .05       0      40     .06       0    98.2    .045       0
   107.8     .06       0  191.11     .05       0  261.11     .06       0
Bank Sta=98.2,107.8
XS Rating Curve= 0 ,0
Exp/Cntr(USF)=0,0
Exp/Cntr=0.3,0.1

Type RM Length L Ch R = 1 ,2742    ,100.1,104,106.9
XS GIS Cut Line= 4
2202155.96967624749399.1150576222202235.52152981749374.845000601
2202277.31996135749279.1131090172202319.11839289 749214.39295696
#Sta/Elev= 30
       0 1420.71    33.7  1418.9      53 1417.54    83.2  1416.1   104.8 1416.14
   112.3 1415.92   115.5 1415.93   127.5  1415.3   136.6 1415.09   146.1 1414.71
   150.5 1413.54   154.41412.062   157.8 1411.26   159.2 1411.03   162.6 1412.01
   163.6 1412.28   167.9 1413.89   172.3 1414.59   174.8 1414.82   176.6 1415.13
   185.2 1416.06   188.2  1416.2   223.3 1416.59     228 1416.91   232.8 1417.42
   243.2 1419.23     249 1420.69   251.8 1421.56   256.6 1422.64   264.7 1424.23
#Mann= 5 ,-1,0
       0     .05       0      50     .06       0   154.4    .045       0
   162.6     .06       0  197.63     .05       0
Bank Sta=154.4,162.6
XS Rating Curve= 0 ,0
Exp/Cntr(USF)=0,0
Exp/Cntr=0.3,0.1

Type RM Length L Ch R = 1 ,2639    ,55.3,55.3,55.3
XS GIS Cut Line= 2
2202238.21820282749473.2735651872202424.28863998749273.719763012
#Sta/Elev= 30
       0 1419.79    12.8 1419.31    38.1 1419.28    52.4 1417.51    66.5 1416.51
      85 1415.87   117.5 1415.27   147.8 1414.32   149.5 1414.12   151.4 1413.56
   154.3 1412.09   157.1 1410.86   159.9  1410.6   162.8 1411.06   167.1 1412.09
   171.3 1412.85   176.9 1415.12   180.6 1415.89   193.9 1415.69   202.5 1416.06
   224.4 1415.57   235.3 1415.85   243.4 1415.45   249.2 1415.78   251.7  1416.5
   256.2 1418.77   260.9  1422.1   264.7 1424.36   267.5 1426.22   272.8 1430.26
#Mann= 5 ,-1,0
       0     .05       0      10     .06       0     150     .05       0
   154.3    .045       0   167.1     .05       0
Bank Sta=154.3,167.1
XS Rating Curve= 0 ,0
Exp/Cntr(USF)=0,0
Exp/Cntr=0.3,0.1

Type RM Length L Ch R = 1 ,2583    ,44.2,44.2,44.7
XS GIS Cut Line= 2
 2202260.3652341749523.4344230172202482.09168096749295.715369486
#Sta/Elev= 30
       0 1420.55    25.5 1419.36      59 1418.73   103.3 1415.82   111.8 1415.44
   142.9 1414.81   171.2 1413.72     174 1413.48   177.5 1412.81   181.61411.045
   183.2 1410.53   185.3 1410.56   188.2 1411.07   193.8 1414.12   196.6 1415.12
   199.5  1415.5   210.8  1415.6   219.3 1416.26   224.9 1415.59     232 1415.28
     252 1415.28   257.7 1415.82   261.7 1417.47   270.2 1422.04   275.8 1423.81
   287.9 1426.22   292.2 1427.93   295.6 1429.61   304.1 1434.27   317.8 1438.75
#Mann= 5 ,-1,0
       0     .05       0      60     .06       0   181.6    .045       0
   188.2     .06       0     200     .05       0
Bank Sta=181.6,188.2
XS Rating Curve= 0 ,0
Exp/Cntr(USF)=0,0
Exp/Cntr=0.3,0.1

Type RM Length L Ch R = 1 ,2539    ,65,64.3,64
XS GIS Cut Line= 2
2202302.02084515749533.7311639812202525.07419584749324.259516145
#Sta/Elev= 30
       0 1419.48    46.9 1417.35    57.8 1416.58   115.1  1414.5   145.6 1413.15
   149.1 1412.78   151.1 1412.35   153.51411.366   156.6 1410.33   157.6 1410.25
   160.4 1410.41   164.4 1411.47   171.7 1414.14   178.5 1415.24     184 1415.39
   222.4 1415.12   228.7 1415.73     234 1416.65   240.4 1418.31   250.9 1421.77
   271.8 1426.76   273.6 1427.38   276.4 1428.76   282.1 1432.63   284.9 1434.03
   287.7    1435   293.4 1436.27   299.3 1438.31   301.9 1438.88     306 1439.22
#Mann= 5 ,-1,0
       0     .06       0     140     .05       0   153.5    .045       0
   164.4     .05       0     270      .1       0
Bank Sta=153.5,164.4
XS Rating Curve= 0 ,0
Exp/Cntr(USF)=0,0
Exp/Cntr=0.3,0.1

Type RM Length L Ch R = 1 ,2475    ,62.2,62.9,63.4
XS GIS Cut Line= 2
2202329.05814906749612.5654780662202566.95650017749360.335900987
#Sta/Elev= 30
       0 1423.03    10.4 1421.71    30.1 1419.95    66.9 1417.25      92 1415.98
   131.1 1414.72   138.6 1414.72   179.4 1412.88   182.9 1412.28   186.71410.895
   188.5 1410.37   191.1 1410.18   195.31410.911     197 1411.35   202.7 1414.37
   208.1  1415.4   220.2 1414.75   237.7  1415.3   261.1 1414.91   274.1 1415.06
   279.6 1415.43   287.6 1417.56   301.7 1423.44   315.9 1428.32   318.1  1429.2
   324.3 1432.62   329.1 1434.51   335.7 1435.88   342.7 1438.23   346.7 1438.84
#Mann= 5 ,-1,0
       0     .06       0   186.7    .045       0   195.3     .06       0
     200     .05       0     250      .1       0
Bank Sta=186.7,195.3
XS Rating Curve= 0 ,0
Exp/Cntr(USF)=0,0
Exp/Cntr=0.3,0.1

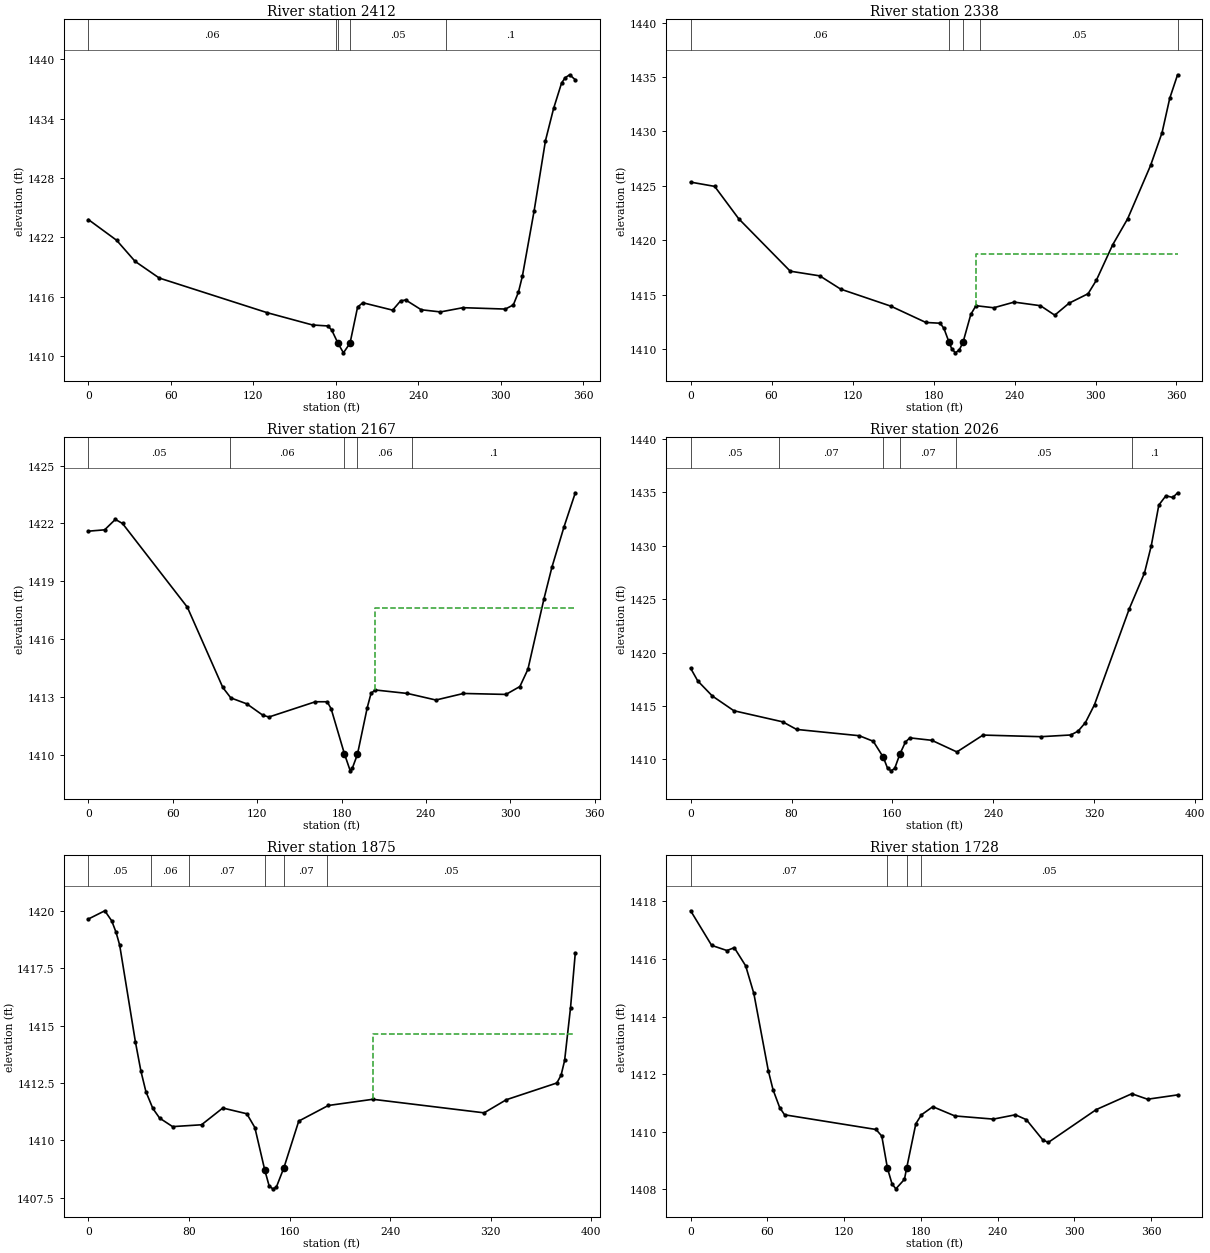
Type RM Length L Ch R = 1 ,2412    ,73.6,73.9,74.2
XS GIS Cut Line= 2
2202369.09416741749644.409231702 2202627.8524141749402.370748646
#Sta/Elev= 30
       0 1423.79    20.6 1421.69      34 1419.56    51.6 1417.87   130.2 1414.36
   163.1 1413.12   174.3 1413.02   177.1  1412.6   181.71411.254   185.6  1410.3
   190.4 1411.28   195.9 1414.93   199.7 1415.37   221.4 1414.62   227.2 1415.56
   230.9 1415.65   242.2 1414.66   256.2 1414.44   272.6 1414.87   303.4 1414.73
   309.2 1415.15   312.9 1416.43   315.8 1418.06   324.3 1424.64   332.6 1431.78
   338.5 1435.03   344.3  1437.6   346.9 1438.14   350.2 1438.44   354.3 1437.93
#Mann= 5 ,-1,0
       0     .06       0     180     .05       0   181.7    .045       0
   190.4     .05       0     260      .1       0
Bank Sta=181.7,190.4
XS Rating Curve= 0 ,0
Exp/Cntr(USF)=0,0
Exp/Cntr=0.3,0.1

Type RM Length L Ch R = 1 ,2338    ,173,170.9,169.1
XS GIS Cut Line= 3
2202413.17532099749711.2887354372202491.07920772749627.392242031
2202676.85001455 749465.59186189
#Sta/Elev= 30
       0 1425.34    17.8 1424.95    35.6 1421.98    73.8 1417.16    95.7 1416.73
   111.2 1415.51   148.3 1413.95   174.3 1412.45   184.9 1412.38   187.7  1411.9
   191.41410.658   193.4 1410.05   196.2 1409.66   199.1 1409.93   201.9 1410.66
   207.6 1413.19   211.4 1413.99   224.6  1413.8   239.7 1414.32   259.2 1413.99
   269.8 1413.12   280.4 1414.22   294.5 1415.09   300.6 1416.32   312.7 1419.58
   323.8 1421.97   340.8 1426.87   349.3 1429.88     355 1433.04   360.8  1435.2
#Mann= 5 ,-1,0
       0     .06       0   191.4    .045       0   201.9     .06       0
  214.49     .05       0  360.84      .1       0
#XS Ineff= 2 , 0
                          211.27         1418.73
Permanent Ineff=
       F       F
Bank Sta=191.4,201.9
XS Rating Curve= 0 ,0
Exp/Cntr(USF)=0,0
Exp/Cntr=0.3,0.1

Type RM Length L Ch R = 1 ,2167    ,139.2,141.3,142.2
XS GIS Cut Line= 3
2202556.93839036749840.1992497952202607.06819314749777.291261996
2202768.26991188749565.959740483
#Sta/Elev= 30
       0  1421.6    11.6 1421.67    19.2 1422.21    24.3    1422    70.4 1417.66
    95.6  1413.5   101.3 1412.96   112.7 1412.65   124.1 1412.06   128.4 1411.97
   161.4 1412.76   169.8 1412.76   172.6  1412.4   182.11410.052   186.2 1409.18
   187.8 1409.34   191.3 1410.03   198.3 1412.46     201  1413.2     204 1413.37
   226.9 1413.19   247.1 1412.85   266.7 1413.19   296.9 1413.14   306.8 1413.55
   312.5 1414.44   323.9 1418.09   329.6 1419.74   338.2 1421.83   346.2 1423.59
#Mann= 5 ,-1,0
       0     .05       0  100.44     .06       0   182.1    .045       0
   191.3     .06       0  230.44      .1       0
#XS Ineff= 2 , 0
                          204.03          1417.6
Permanent Ineff=
       F       F
Bank Sta=182.1,191.3
XS Rating Curve= 0 ,0
Exp/Cntr(USF)=0,0
Exp/Cntr=0.3,0.1

Type RM Length L Ch R = 1 ,2026    ,151.1,150.4,149
XS GIS Cut Line= 2
2202651.34019877749905.0461711182202930.96558388749638.736280539
#Sta/Elev= 30
       0 1418.53     5.6 1417.35    17.2 1415.93    34.3 1414.55      73 1413.51
      84  1412.8   133.7 1412.21   144.8 1411.69   152.71410.206   156.1 1409.17
   158.9 1408.92   161.8 1409.15   165.91410.492   170.3 1411.62   173.8 1412.01
   191.2 1411.78   211.1 1410.69   231.8 1412.27   277.8 1412.12   301.4 1412.28
   307.2 1412.64     313 1413.44   320.2 1415.12   347.8 1424.11   359.8 1427.45
   365.2    1430   371.2 1433.82   376.8 1434.69   382.3 1434.53   386.1 1434.97
#Mann= 6 ,-1,0
       0     .05       0      70     .07       0   152.7    .045       0
   165.9     .07       0     210     .05       0     350      .1       0
Bank Sta=152.7,165.9
XS Rating Curve= 0 ,0
Exp/Cntr(USF)=0,0
Exp/Cntr=0.3,0.1

Type RM Length L Ch R = 1 ,1875    ,150.8,147.5,142.8
XS GIS Cut Line= 2
2202762.70615301750018.8331243662203025.38454508749734.365741247
#Sta/Elev= 30
       0 1419.64    13.1    1420    18.6 1419.56      22 1419.07    24.9 1418.51
    37.5 1414.27    41.8 1413.02    45.8 1412.12    51.3 1411.39    56.7 1410.97
      67  1410.6      90 1410.68   106.9 1411.41     126 1411.16   132.4 1410.56
   140.31408.705   143.7 1408.03   146.6 1407.89   149.4 1407.95   155.5 1408.81
   167.3 1410.84   190.8 1411.52   226.2 1411.79   314.7  1411.2   332.3 1411.77
   372.5  1412.5   375.9 1412.84   378.7 1413.48   383.4 1415.78   387.2 1418.17
#Mann= 6 ,-1,0
       0     .05       0      50     .06       0      80     .07       0
   140.3    .045       0   155.5     .07       0     190     .05       0
#XS Ineff= 2 , 0
                          226.03         1414.63
Permanent Ineff=
       F       F
Bank Sta=140.3,155.5
XS Rating Curve= 0 ,0
Exp/Cntr(USF)=0,0
Exp/Cntr=0.3,0.1

Type RM Length L Ch R = 1 ,1728    ,146.5,145.1,142.2
XS GIS Cut Line= 3
2202913.08723731750135.987506853 2202995.6539713749962.990540406
2203064.45958295 749787.04476203
#Sta/Elev= 30
       0 1417.67    16.4 1416.47    28.4 1416.29    34.1 1416.39      43 1415.76
    49.4  1414.8    60.7 1412.12    64.4 1411.46    69.6 1410.84    73.4 1410.59
   144.9 1410.08   149.4 1409.85   153.8 1408.74   157.4 1408.19   160.4 1408.02
   167.1 1408.35   168.81408.735     176 1410.28   180.4 1410.59   189.3 1410.87
   206.5 1410.55   236.6 1410.44   253.8 1410.59   262.4 1410.42   275.2 1409.72
   279.5 1409.63     317 1410.77   344.8 1411.32   357.1 1411.13   380.6 1411.28
#Mann= 4 ,-1,0
       0     .07       0   153.8    .045       0   168.8     .07       0
     180     .05       0
Bank Sta=153.8,168.8
XS Rating Curve= 0 ,0
Exp/Cntr(USF)=0,0
Exp/Cntr=0.3,0.1

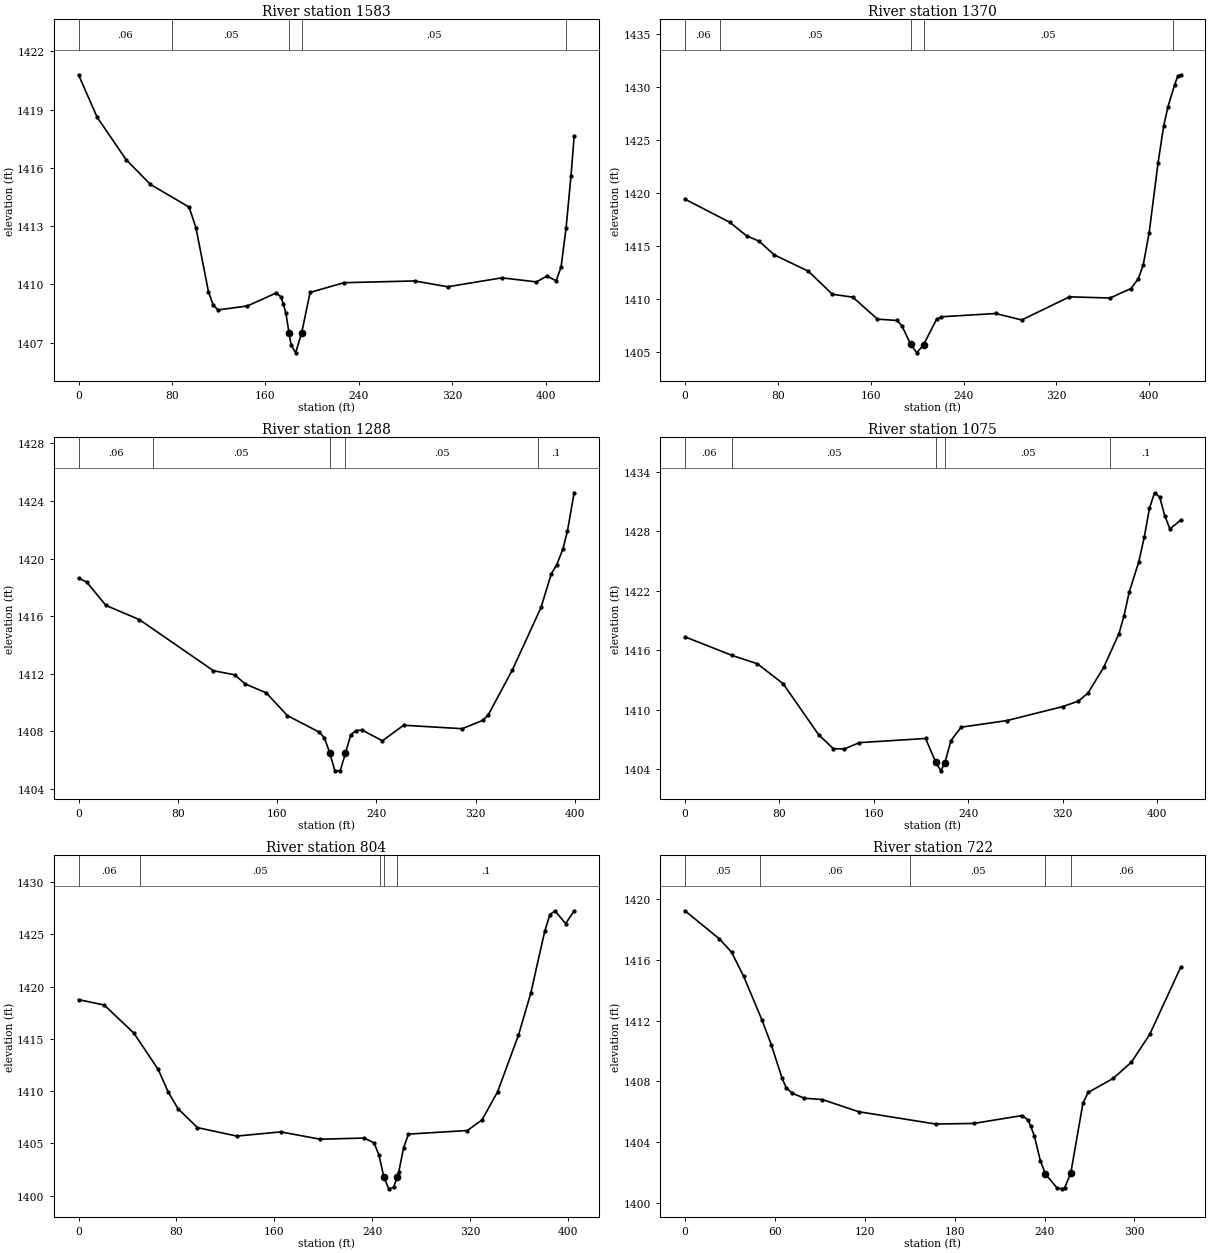
Type RM Length L Ch R = 1 ,1583    ,209.4,212.1,210.4
XS GIS Cut Line= 3
2203068.39133219 750216.588366222203130.31638268 749987.56397314
2203191.25849586749810.635257455
#Sta/Elev= 30
       0 1420.79      16  1418.6    40.8 1416.42    61.5 1415.15    94.7 1413.98
   100.5 1412.93   111.3 1409.62   115.4 1408.92   119.6 1408.69   144.4 1408.89
   169.3 1409.56   173.4 1409.36   175.5 1408.97   177.6 1408.51   180.21407.525
     182 1406.89   185.9 1406.48   191.11407.518   198.3 1409.59   227.3 1410.09
   287.8 1410.18   316.1 1409.88   362.5 1410.34   392.1 1410.13   401.1 1410.43
     409 1410.19   413.2  1410.9   417.5 1412.92   421.7  1415.6   424.4 1417.63
#Mann= 5 ,-1,0
       0     .06       0      80     .05       0   180.2    .045       0
   191.1     .05       0  417.25      .1       0
Bank Sta=180.2,191.1
XS Rating Curve= 0 ,0
Exp/Cntr(USF)=0,0
Exp/Cntr=0.3,0.1

Type RM Length L Ch R = 1 ,1370    ,82.9,82.8,83
XS GIS Cut Line= 2
2203246.57446014750277.5707432782203388.37482377749874.775507445
#Sta/Elev= 30
       0  1419.4    38.6 1417.22      53 1415.95      64 1415.43    76.7 1414.16
   106.4  1412.6     127 1410.43   144.6 1410.16   165.8 1408.09   182.8 1407.96
     187 1407.43   194.4 1405.72   199.7 1404.91   205.51405.674   216.7 1408.06
   220.9 1408.31   267.6 1408.62   290.1 1408.01   331.2 1410.19   366.2 1410.08
   384.2 1410.97   390.6 1411.91   394.8 1413.21   399.9 1416.25   407.5 1422.78
   412.4 1426.31     416 1428.07   421.8 1430.19   424.5 1430.99     427 1431.13
#Mann= 5 ,-1,0
       0     .06       0      30     .05       0   194.4    .045       0
   205.5     .05       0     420      .1       0
Bank Sta=194.4,205.5
XS Rating Curve= 0 ,0
Exp/Cntr(USF)=0,0
Exp/Cntr=0.3,0.1

Type RM Length L Ch R = 1 ,1288    ,212.4,212.7,212.8
XS GIS Cut Line= 2
2203321.95692323750303.3005074852203458.74336703749928.045661668
#Sta/Elev= 30
       0 1418.64     6.5 1418.37    22.1 1416.74    49.1 1415.75   108.7  1412.2
   125.7 1411.92   134.4 1411.28   151.3 1410.66   168.3 1409.08   193.8 1407.94
   198.1 1407.55   202.4  1406.5   206.6 1405.24   210.9 1405.25   215.1 1406.47
   219.4 1407.75   223.6 1408.04   228.4 1408.08   244.9 1407.33     262 1408.41
   309.2 1408.17   325.8 1408.75   330.1 1409.12   349.7 1412.27   372.7  1416.6
   380.9 1418.92   385.4 1419.58   390.3 1420.65   393.9 1421.88   399.4 1424.57
#Mann= 5 ,-1,0
       0     .06       0      60     .05       0   202.4    .045       0
   215.1     .05       0     370      .1       0
Bank Sta=202.4,215.1
XS Rating Curve= 0 ,0
Exp/Cntr(USF)=0,0
Exp/Cntr=0.3,0.1

Type RM Length L Ch R = 1 ,1075    ,272.9,270.7,266.4
XS GIS Cut Line= 2
2203509.31931984 750386.25054869 2203665.7929385749996.731115018
#Sta/Elev= 30
       0 1417.35      40 1415.47    61.3 1414.63    83.1 1412.62   113.2 1407.46
   125.7 1406.05   134.8 1406.01   147.7 1406.66   203.8 1407.08   212.4 1404.67
   216.7 1403.81   220.21404.652   225.3 1406.87   233.9 1408.22   272.7 1408.89
   319.8  1410.3   333.1 1410.85   341.3 1411.66   354.6 1414.26   367.6 1417.68
   371.9  1419.5   376.2 1421.85   384.4 1424.95   389.1 1427.49   393.4 1430.34
   397.7 1431.91     402 1431.49   406.4 1429.58   410.7 1428.26   419.8 1429.14
#Mann= 5 ,-1,0
       0     .06       0      40     .05       0   212.4    .045       0
   220.2     .05       0     360      .1       0
Bank Sta=212.4,220.2
XS Rating Curve= 0 ,0
Exp/Cntr(USF)=0,0
Exp/Cntr=0.3,0.1

Type RM Length L Ch R = 1 ,804     ,81.2,82.3,83.2
XS GIS Cut Line= 4
2203842.32693174750494.1362911792203836.77822186  750418.3039228
 2203853.4243515750163.0632682572203879.31833095 750094.62917972
#Sta/Elev= 30
       0 1418.75      21 1418.23    45.1 1415.56    65.1 1412.07    73.2 1409.94
    81.2 1408.32    97.2  1406.5   129.3 1405.69   165.3 1406.09   197.4 1405.39
   233.5  1405.5   241.5 1405.03   245.5 1403.88   249.4 1401.81   253.5 1400.64
   257.5 1400.77   260.41401.814   261.6 1402.21   265.6 1404.56   269.6 1405.88
   317.7 1406.22   329.7 1407.24   342.4 1409.92   359.5 1415.35   369.5 1419.34
   380.9 1425.27   385.2 1426.89   389.4 1427.24     398 1426.02     405 1427.25
#Mann= 5 ,-1,0
       0     .06       0      50     .05       0  246.04      .1       0
   249.4    .045       0   260.4      .1       0
Bank Sta=249.4,260.4
XS Rating Curve= 0 ,0
Exp/Cntr(USF)=0,0
Exp/Cntr=0.3,0.1

Type RM Length L Ch R = 1 ,722     ,101.6,110.1,116.9
XS GIS Cut Line= 3
2203893.91812569750495.9769076432203922.62568353750291.976995385
2203942.61774376750168.800108169
#Sta/Elev= 30
       0 1419.22      23 1417.37    31.1  1416.5    39.2  1414.9    51.3 1412.06
    57.6 1410.42    64.7 1408.24    67.5  1407.6    71.5 1407.23    79.6  1406.9
    91.7 1406.81   115.9 1406.01   167.4  1405.2   192.7 1405.24   225.1 1405.76
   229.1 1405.45   230.7 1405.06   233.2 1404.41   237.2 1402.78   240.6 1401.91
   248.2 1401.01   251.6 1400.94   253.4    1401   257.5 1401.99   265.6 1406.57
   269.1 1407.28   285.8  1408.2     298 1409.27   310.2  1411.1   330.8  1415.5
#Mann= 5 ,-1,0
       0     .05       0      50     .06       0     150     .05       0
   240.6    .045       0   257.5     .06       0
Bank Sta=240.6,257.5
XS Rating Curve= 0 ,0
Exp/Cntr(USF)=0,0
Exp/Cntr=0.3,0.1