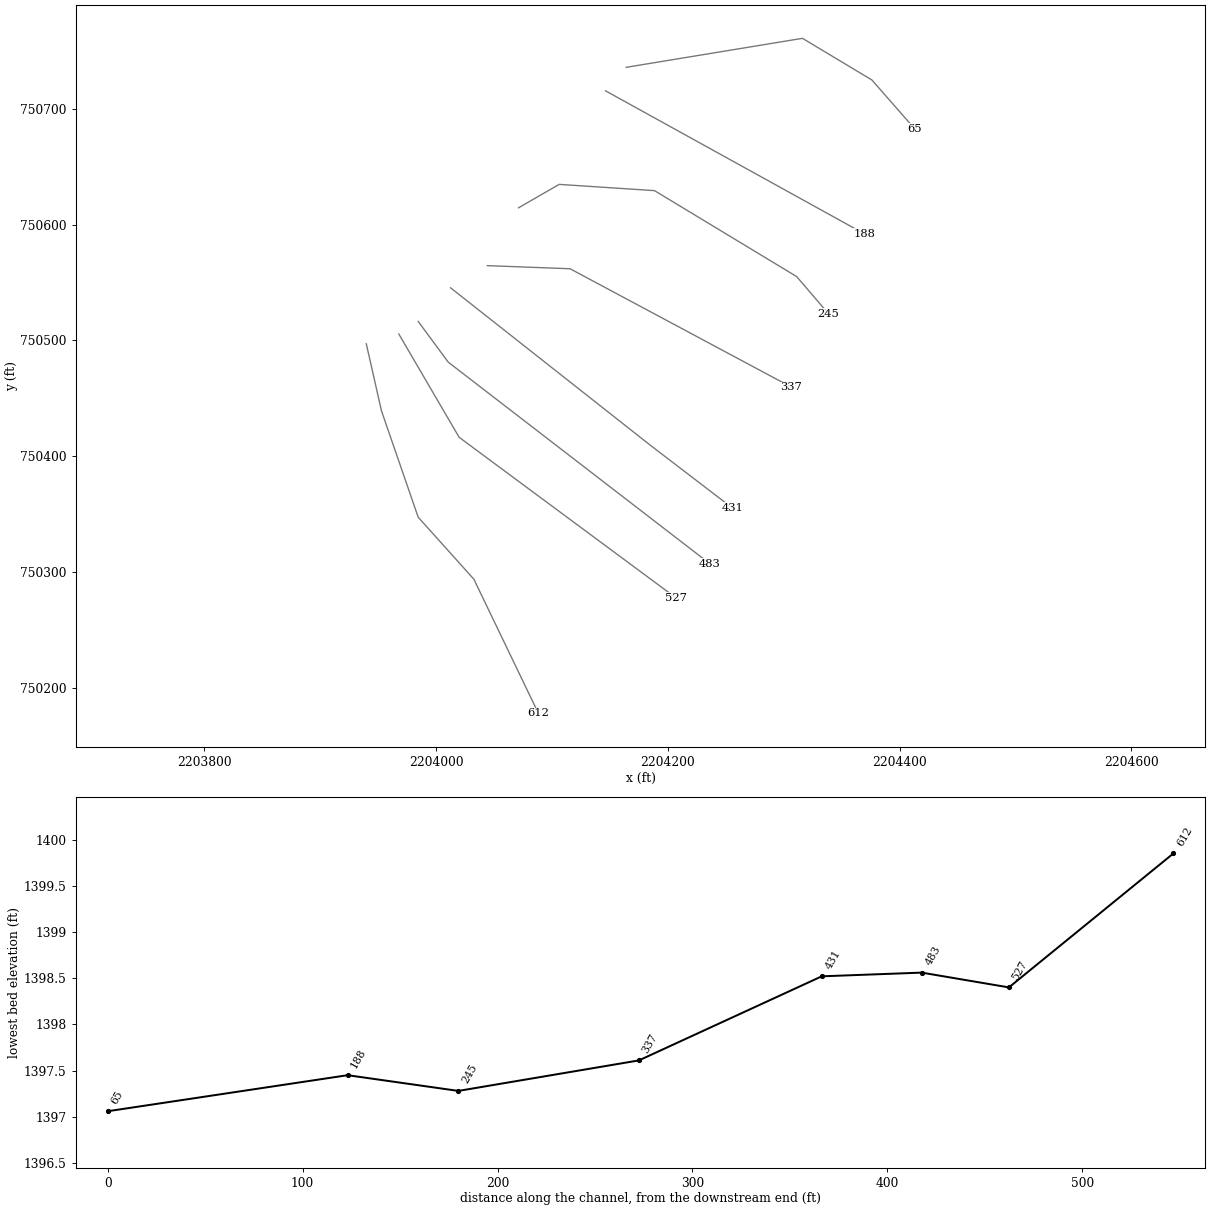
HEC-RAS study PECKSRNT2.prj: PECKSRNT2

--- PECKSRNT2.g01 (geometry) --- (continued)

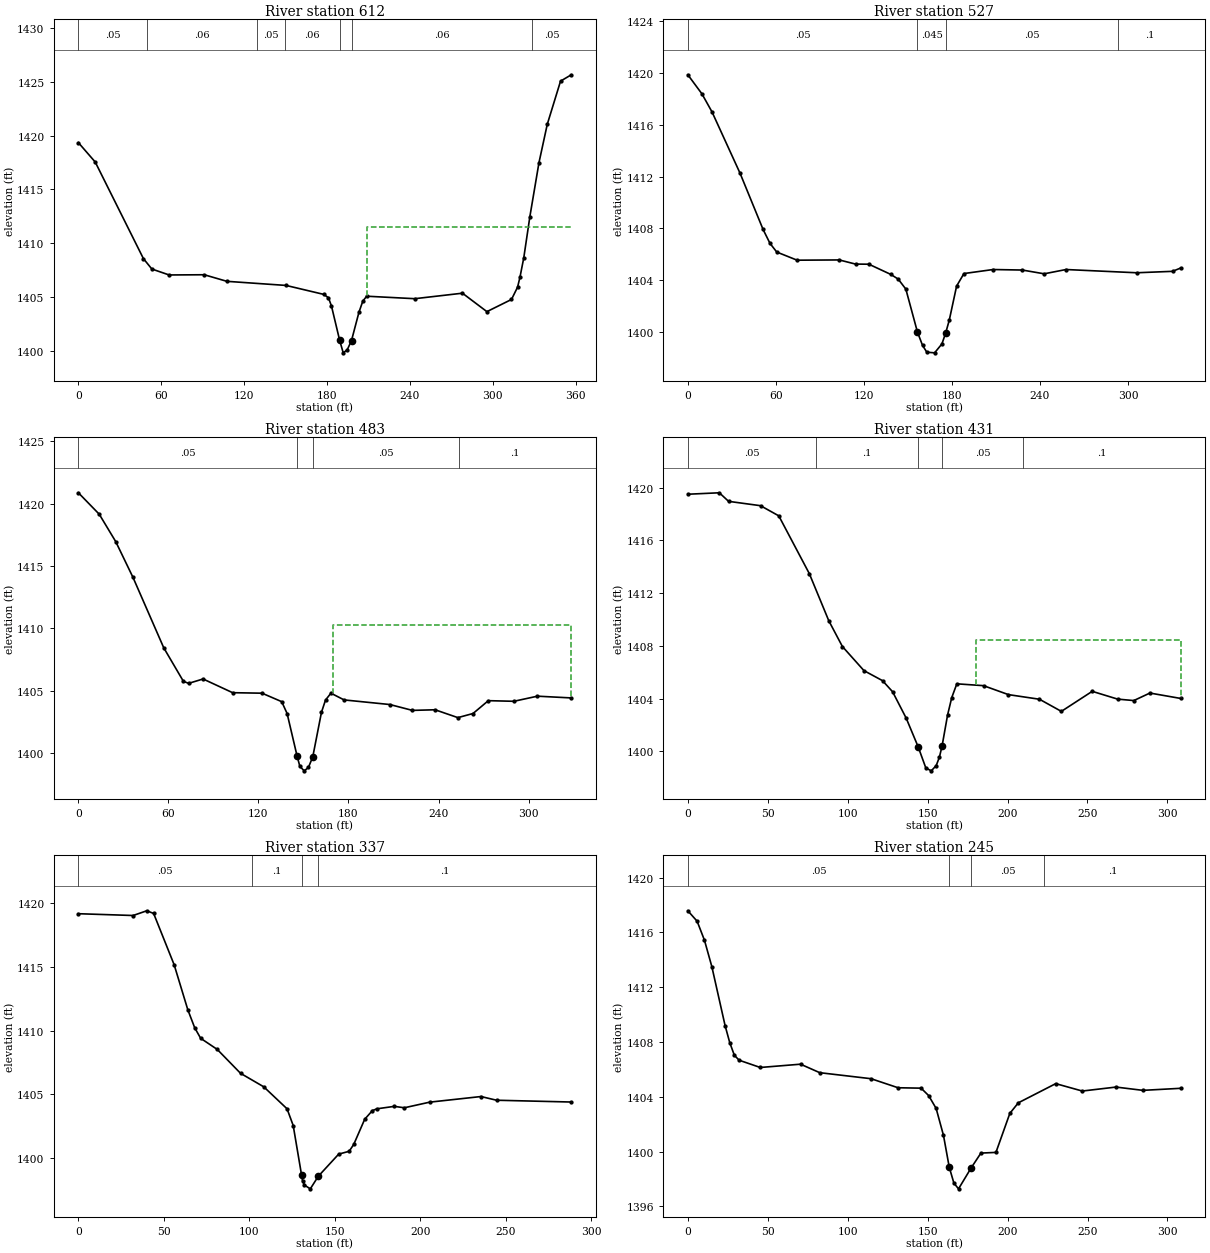
Type RM Length L Ch R = 1 ,612     ,82.6,84.4,86.4
XS GIS Cut Line= 5
2203939.78853346750497.0690602092203952.89436425750439.184974214
2203984.56678866750347.4441586742204032.62150156750293.928682942
2204088.32128243750178.160510951
#Sta/Elev= 30
       0 1419.34    12.2 1417.54    47.1 1408.58    53.2 1407.62    65.7 1407.07
    91.1 1407.09   107.5 1406.48   150.3  1406.1   177.6 1405.27     181 1404.96
   183.2 1404.19   189.1 1401.02   191.7 1399.85   194.6 1400.13   197.7 1400.99
   203.1 1403.62   205.9 1404.65   208.7  1405.1   243.5 1404.87     278 1405.38
   295.7 1403.67   313.5  1404.8   317.9 1405.94   319.6 1406.84   322.4 1408.67
   326.8 1412.48   333.4 1417.49   339.4 1421.04     349 1425.04   356.8 1425.63
#Mann= 7 ,-1,0
       0     .05       0      50     .06       0  129.35     .05       0
  149.35     .06       0   189.1    .045       0   197.7     .06       0
  328.33     .05       0
#XS Ineff= 2 , 0
                           208.7         1411.49
Permanent Ineff=
       F       F
Bank Sta=189.1,197.7
XS Rating Curve= 0 ,0
Exp/Cntr(USF)=0,0
Exp/Cntr=0.3,0.1

Type RM Length L Ch R = 1 ,527     ,44.9,44.7,44.5
XS GIS Cut Line= 3
2203967.85619913750505.5043382382204019.92099324750416.376470359
2204207.00127037750277.831170783
#Sta/Elev= 30
       0 1419.86     9.6 1418.39    16.5 1416.99    35.6 1412.26    51.3 1407.92
      56 1406.85    60.6 1406.18    74.5 1405.55   103.2 1405.57   114.3 1405.25
   123.4 1405.24   138.4 1404.45   143.4 1404.09   148.6 1403.32   156.51400.008
     160 1398.97   162.9 1398.45   168.2  1398.4   173.2 1399.09   175.8 1399.95
   178.2 1400.92   183.2 1403.55   188.2 1404.52   208.1 1404.83     228 1404.79
   242.9  1404.5   257.8 1404.83   305.9 1404.58   330.4 1404.69     336 1404.95
#Mann= 4 ,-1,0
       0     .05       0   156.5    .045       0   175.8     .05       0
  293.22      .1       0
Bank Sta=156.5,175.8
XS Rating Curve= 0 ,0
Exp/Cntr(USF)=0,0
Exp/Cntr=0.3,0.1

Type RM Length L Ch R = 1 ,483     ,51,51.3,51.4
XS GIS Cut Line= 3
2203984.56024116750516.4047646922204010.45422061750481.262935444
2204236.10175579750307.403359161
#Sta/Elev= 30
       0 1420.87    13.9 1419.15    24.9 1416.95    36.4 1414.08    56.9 1408.43
      70 1405.74    73.5 1405.58    83.1 1405.93   102.8 1404.83   122.4 1404.79
   135.5 1404.11   139.1 1403.16   145.8 1399.72   147.6 1398.92   150.5 1398.56
   153.3 1398.83   156.2 1399.68     162 1403.26   164.7 1404.24   168.3 1404.79
   177.1 1404.25   207.6 1403.88   222.6 1403.41   237.7 1403.46   252.9 1402.83
     263 1403.16   273.2 1404.19   290.2 1404.14   305.9 1404.55   328.5 1404.41
#Mann= 4 ,-1,0
       0     .05       0   145.8    .045       0   156.2     .05       0
  253.65      .1       0
#XS Ineff= 2 , 0
                           169.4         1410.23
Permanent Ineff=
       F       F
Bank Sta=145.8,156.2
XS Rating Curve= 0 ,0
Exp/Cntr(USF)=0,0
Exp/Cntr=0.3,0.1

Type RM Length L Ch R = 1 ,431     ,91.2,93.8,95.6
XS GIS Cut Line= 3
2204012.51708462750545.3689342262204185.28797549750409.222287507
2204255.53624793750355.487134876
#Sta/Elev= 30
       0  1419.5    19.7 1419.61    25.5 1418.96    45.5 1418.63    56.9 1417.86
      76 1413.48    88.2  1409.9    96.7 1407.95   110.2 1406.12   121.8 1405.36
   128.1 1404.52   136.6 1402.52   144.11400.341   148.9 1398.74   152.3 1398.52
   155.4 1398.92   157.4 1399.56   159.11400.427   162.5 1402.75   165.1 1404.07
   168.3 1405.12     185 1404.98   200.6  1404.3     220 1403.95   233.7 1403.03
     253 1404.55   268.9 1403.96     279 1403.85   289.1 1404.42   308.4 1404.01
#Mann= 5 ,-1,0
       0     .05       0      80      .1       0   144.1    .045       0
   159.1     .05       0     210      .1       0
#XS Ineff= 2 , 0
                          180.06         1408.46
Permanent Ineff=
       F       F
Bank Sta=144.1,159.1
XS Rating Curve= 0 ,0
Exp/Cntr(USF)=0,0
Exp/Cntr=0.3,0.1

Type RM Length L Ch R = 1 ,337     ,93.1,92.6,92.5
XS GIS Cut Line= 3
2204044.19420532750564.5117052652204115.65603988750561.815032262
 2204306.7185879750459.616723092
#Sta/Elev= 30
       0 1419.16      32 1419.02      40 1419.39      44 1419.18      56 1415.16
      64 1411.63      68 1410.23    71.5  1409.4    81.2 1408.53    94.8 1406.66
   108.4  1405.6     122 1403.88   125.6 1402.57   130.51398.683   131.1 1398.22
   132.2  1397.9   135.6 1397.61   140.3  1398.6   152.2 1400.33   158.3 1400.55
     161 1401.09   167.4 1403.06   171.9 1403.74   174.6 1403.88   184.7 1404.07
   190.6 1403.96   205.4  1404.4   235.4 1404.84   244.5 1404.55   288.2 1404.41
#Mann= 4 ,-1,0
       0     .05       0  101.51      .1       0   130.5    .045       0
   140.3      .1       0
Bank Sta=130.5,140.3
XS Rating Curve= 0 ,0
Exp/Cntr(USF)=0,0
Exp/Cntr=0.3,0.1

Type RM Length L Ch R = 1 ,245     ,56.4,56.8,57.3
XS GIS Cut Line= 5
2204071.16093534750614.4001558082204106.21768437750634.625203326
2204188.46621094750629.2318573212204311.16483255750555.073349757
2204338.48693685750523.153420987
#Sta/Elev= 30
       0 1417.58     5.8 1416.82    10.4 1415.43      15 1413.51    23.3  1409.2
    26.2 1407.96    29.1 1407.03    32.1 1406.67    45.3 1406.14    70.5 1406.38
    82.5 1405.76   114.6 1405.32   131.5 1404.66   145.9 1404.63   150.6 1404.09
   155.3 1403.15   159.9 1401.18   163.5 1398.86   166.4  1397.7   169.3 1397.28
   177.1 1398.79   183.3 1399.89   192.7 1399.94   201.4 1402.79   206.7 1403.56
   230.1 1404.96   246.7 1404.42   267.8 1404.71   284.6 1404.47   308.3 1404.62
#Mann= 4 ,-1,0
       0     .05       0   163.5    .045       0   177.1     .05       0
   222.9      .1       0
Bank Sta=163.5,177.1
XS Rating Curve= 0 ,0
Exp/Cntr(USF)=0,0
Exp/Cntr=0.3,0.1

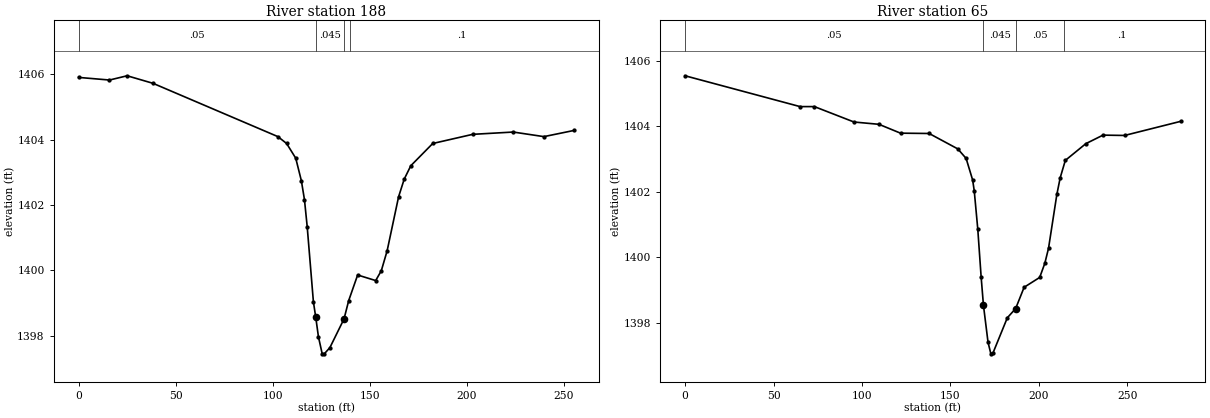
Type RM Length L Ch R = 1 ,188     ,123.1,123.1,123.1
XS GIS Cut Line= 2
2204146.29832277750715.3136880362204369.84179018750591.817646601
#Sta/Elev= 30
       0  1405.9    15.9 1405.82      25 1405.95    38.3 1405.72   102.7 1404.09
   107.2 1403.88   111.9 1403.43   114.8 1402.74   116.4 1402.16   117.8 1401.34
     121 1399.04   122.21398.571   123.6 1397.97   125.5 1397.46   126.6 1397.45
   129.5 1397.64   136.8 1398.52   139.2 1399.08   143.8 1399.86   153.1 1399.69
     156 1399.99     159  1400.6   164.9 1402.25   167.8 1402.79   171.2  1403.2
   182.5 1403.88   203.1 1404.16     224 1404.23   239.8 1404.09   255.4 1404.28
#Mann= 4 ,-1,0
       0     .05       0   122.2    .045       0   136.8     .05       0
     140      .1       0
Bank Sta=122.2,136.8
XS Rating Curve= 0 ,0
Exp/Cntr(USF)=0,0
Exp/Cntr=0.3,0.1

Type RM Length L Ch R = 1 ,65      ,,,
XS GIS Cut Line= 4
2204164.01505445750735.6358214372204316.17051478 750760.64767793
 2204376.0947543750724.693134221 2204413.0914587750682.485626389
#Sta/Elev= 30
       0 1405.54      65  1404.6    73.1  1404.6    95.5 1404.13   109.6 1404.06
   121.8 1403.79     138 1403.78   154.2 1403.31   158.9 1403.02   162.6 1402.36
   163.5 1402.03   165.5 1400.86   167.4  1399.4   168.7 1398.54   171.3 1397.41
   172.9 1397.06   174.2  1397.1   182.2 1398.16   186.9 1398.44   191.7 1399.09
   200.5 1399.39   203.4 1399.82   205.5 1400.28   210.2 1401.92   212.1 1402.43
     215 1402.96   226.6 1403.47   236.3 1403.73   248.5 1403.72   280.2 1404.15
#Mann= 4 ,-1,0
       0     .05       0   168.7    .045       0   186.9     .05       0
   214.2      .1       0
Bank Sta=168.7,186.9
XS Rating Curve= 0 ,0
Exp/Cntr(USF)=0,0
Exp/Cntr=0.3,0.1
LCMann Table=0

Chan Stop Cuts=-1
Use User Specified Reach Order=0
Composite Channel Slope=5